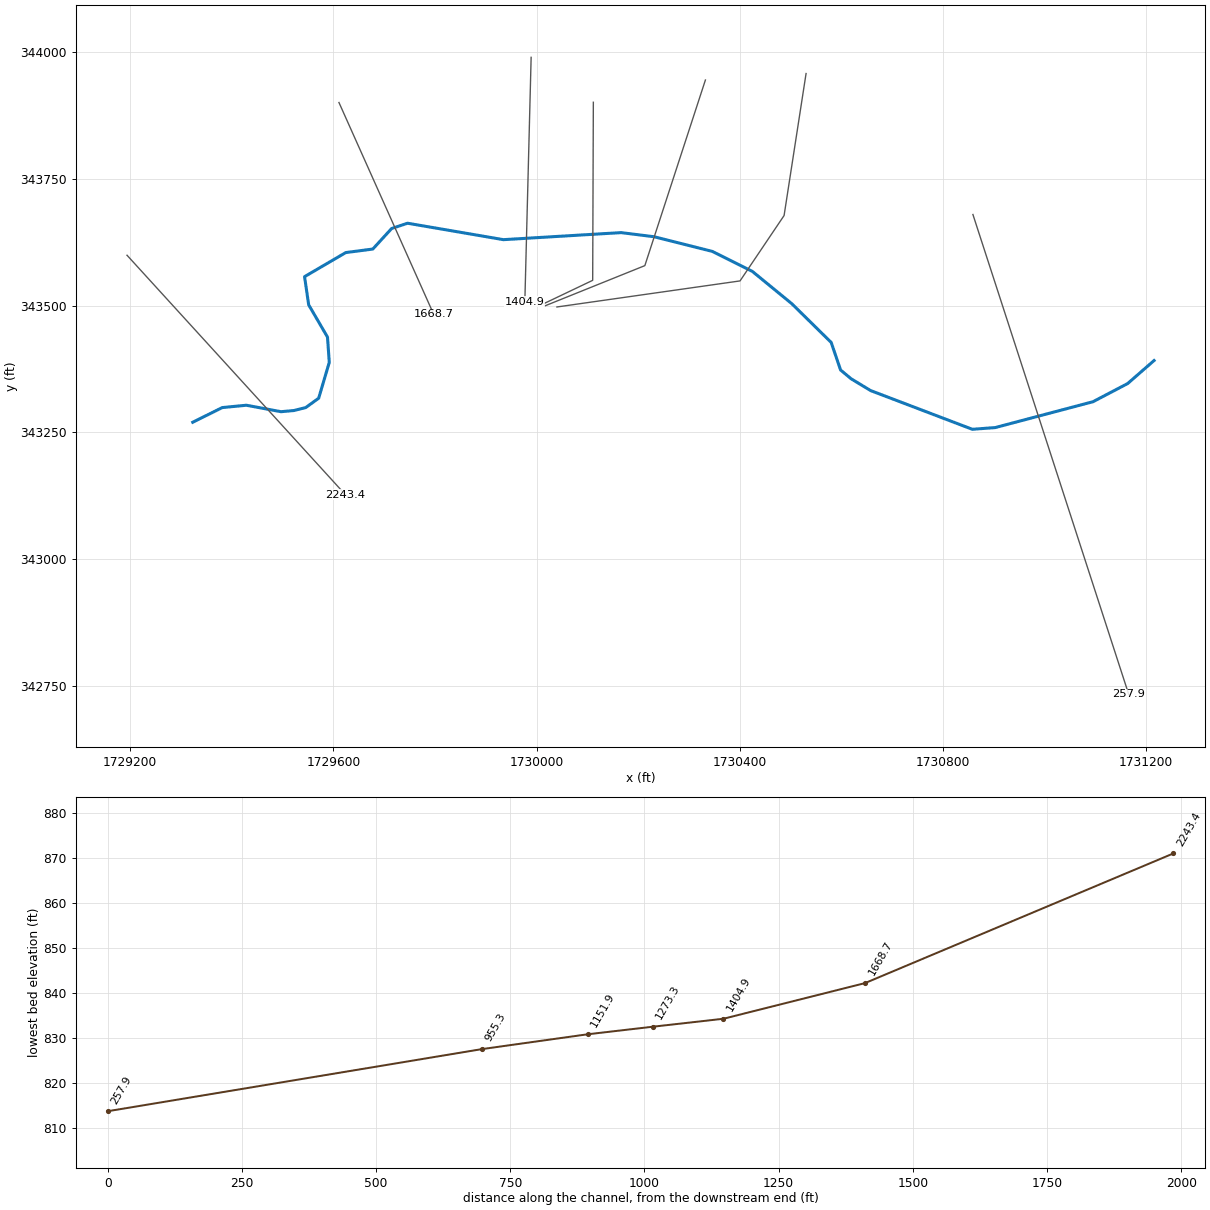
--- ROCKHSFRK.prj (project) ---

Proj Title=ROCKHSFRK
Current Plan=p01
Default Exp/Contr=0,0
English Units
Geom File=g01
Flow File=f01
Plan File=p01
BEGIN DESCRIPTION:
END DESCRIPTION:
DSS Export Rating Curves= 0
DSS Export Rating Curve Sorted= 0
DSS Export Volume Flow Curves= 0
DXF OffsetX= 0
DXF OffsetY= 0
DXF ScaleX= 0
DXF ScaleY= 0

--- ROCKHSFRK.p01 (plan) ---

Plan Title=Floodplain
Program Version=4.00
Geom File=g01
Flow File=f01
K Sum by GR=0
Std Step Tol=0.01
Critical Tol=0.01
Num of Std Step Trials=20
Max Error Tol=0.3
Flow Tol Ratio=0.001
Split Flow NTrial=30
Split Flow Tol=0.02
Split Flow Ratio=0.02
Log Output Level=0
Friction Slope Method=1
Unsteady Friction Slope Method=2
Unsteady Bridges Friction Slope Method=1
Global Log Level=0
CheckData=False
Run HTab=0
Run UNet=0
Run PostProcess=0
UNET Theta=0
UNET Theta Warmup=0
UNET ZTol=0
UNET ZSATol=0
UNET MxIter=0
UNET MaxInSteps=0
UNET DtIC=0
UNET DtMin=0
UNET MaxCRTS=0
UNET WFStab=0
UNET SFStab=0
UNET WFX=0
UNET SFX=0
UNET DSS MLevel=0
UNET DZMax Abort=0
UNET Convert EG Bridges=0
UNET Use Existing IB Tables=0
UNET Froude Limit=0
UNET Froude Power=0
Write IC File=0
Echo Input=False
Echo Output=False
Write Detailed=0

--- ROCKHSFRK.f01 (steady flow) ---

Flow Title=NFF Regression Equation
Program Version=4.00
Number of Profiles=1
Profile Names=P100yr
River Rch & RM=ROCKHSFRK,Main      ,2243.4
1010.524
River Rch & RM=ROCKHSFRK,Main      ,1668.7
1016.146
River Rch & RM=ROCKHSFRK,Main      ,1404.9
1128.290
River Rch & RM=ROCKHSFRK,Main      ,257.9
1138.939
Boundary for River Rch & Prof#=ROCKHSFRK,Main      ,1
Up Type=0
Dn Type=3
Dn Slope=0.035879

--- ROCKHSFRK.g01 (geometry) ---

Geom Title=USGS 10m DEM
Program Version=4.10

River Reach=ROCKHSFRK       ,Main
Reach XY= 30
      1729323.24      343269.812     1729381.151      343298.768
     1729428.637      343303.401     1729496.971       343290.66
     1729522.451      343292.977     1729545.616      343298.768
     1729571.096      343317.299     1729591.944      343387.949
     1729588.469      343437.752     1729551.407      343501.453
     1729543.299      343557.047     1729624.373      343604.533
     1729677.651      343611.483     1729714.713       343652.02
     1729745.985      343662.444     1729934.772      343630.014
     1730166.412      343643.912     1730231.272      343635.805
     1730345.934       343606.85     1730424.692      343567.471
     1730502.291       343503.77     1730579.891      343427.328
     1730598.422      343372.893      1730619.27       343355.52
      1730657.49      343332.356      1730857.86      343255.914
      1730903.03      343259.389     1731095.291       343310.35
     1731163.625      343346.254     1731215.472      343391.592

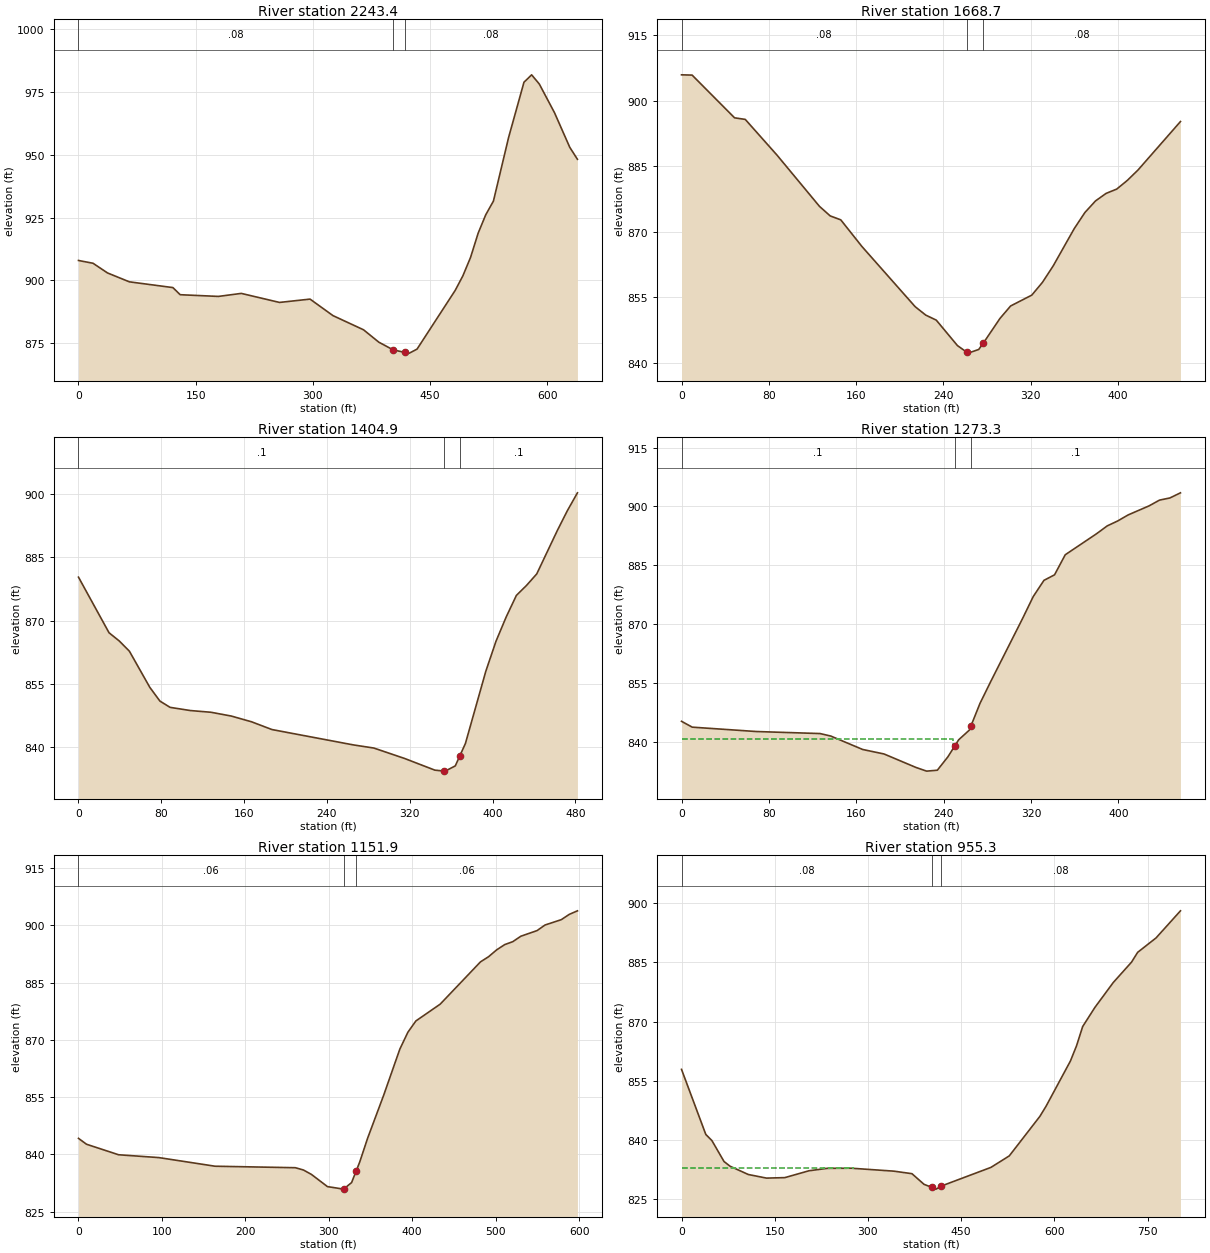
Type RM Length L Ch R = 1 ,2243.4  ,591.6,574.7,556.1
XS GIS Cut Line= 3
     1729193.828       343599.29     1729281.419      343503.041
     1729623.528      343127.118
#Sta/Elev= 30
       0  907.93    18.6  906.82    37.2  902.96    65.1  899.44   120.8  897.15
   130.1  894.32     179  893.64   208.3  894.84   257.2  891.25   296.3  892.57
   325.6  886.01   364.7  880.38   384.3  875.45   402.7  872.38   417.7  871.38
   423.4   871.1   433.2   872.7     482  896.04   491.8  901.81   501.6  909.11
   511.4  918.81   521.1   926.1   530.9  931.52   550.4  956.91     570  978.78
   579.8  981.72   589.6  978.07   609.1  966.64   628.6   952.9   638.4  948.15
#Mann= 3 , 0 , 0
       0     .08       0   402.7    .045       0   417.7     .08       0
Bank Sta=402.7,417.7
XS Rating Curve= 0 ,0
Exp/Cntr=0.3,0.1

Type RM Length L Ch R = 1 ,1668.7  ,273.8,263.7,253.7
XS GIS Cut Line= 2
     1729611.014      343900.565     1729797.304      343483.177
#Sta/Elev= 30
       0  905.89     9.7  905.83    48.6  896.06    58.4   895.7    87.5  887.53
   126.4  875.82   136.2  873.64   145.9  872.74   165.3  866.64     214   852.9
   223.7  850.97   233.4  849.81   252.8  843.99   261.4  842.47   262.6  842.27
   272.3  843.11   276.4  844.53   291.8  850.22   301.5  853.05   320.9  855.53
   330.6  858.43   340.4  862.17   359.8  870.74   369.6  874.43   379.3  877.07
     389  878.79   398.7  879.77   408.4  881.75   418.2  884.13   457.1  895.21
#Mann= 3 , 0 , 0
       0     .08       0   261.4    .045       0   276.4     .08       0
Bank Sta=261.4,276.4
XS Rating Curve= 0 ,0
Exp/Cntr=0.3,0.1

Type RM Length L Ch R = 1 ,1404.9  ,131.2,131.6,132.1
XS GIS Cut Line= 2
     1729989.302      343989.691      1729976.91      343507.806
#Sta/Elev= 30
       0  880.31    29.5  867.14    39.4  865.19    49.2  862.76    68.9   854.2
    78.7  850.94    88.5  849.46   108.2   848.7   127.9   848.3   147.6   847.4
   167.2  846.04   186.9   844.2   265.6  840.56   285.3  839.82   314.8  837.37
   344.3  834.58   353.3  834.37   354.2  834.35     364  835.59   368.3  837.92
   373.8  840.91   393.5  858.02   403.3  865.11   413.2  870.89     423  875.98
   432.9  878.37   442.7  881.08   462.4  891.27   472.2  896.03     482  900.29
#Mann= 3 , 0 , 0
       0      .1       0   353.3    .045       0   368.3      .1       0
Bank Sta=353.3,368.3
XS Rating Curve= 0 ,0
Exp/Cntr=0.3,0.1

Type RM Length L Ch R = 1 ,1273.3  ,128.4,121.4,114.4
XS GIS Cut Line= 3
      1730111.75      343901.055     1730110.442      343549.779
     1730015.202      343504.243
#Sta/Elev= 30
       0  845.27     9.8  843.78    68.3  842.67   126.8  842.15   136.6  841.52
   165.9  838.09   185.4  836.95   214.7  833.51   224.4  832.58   234.2  832.81
   243.9  836.23   250.1  838.96   253.7  840.55   263.5  843.03   265.1  844.17
   273.2   849.8     283  855.35   312.2  871.43     322  877.04   331.8  881.17
   341.5  882.58   351.3  887.69   380.1  893.07   389.7  895.04   399.3   896.3
   408.9  897.84     428  900.14   437.6  901.61   447.2  902.17   456.8  903.47
#Mann= 3 , 0 , 0
       0      .1       0   250.1    .045       0   265.1      .1       0
#XS Ineff= 2 , 0
          248.48  840.89
Permanent Ineff=
       F       F
Bank Sta=250.1,265.1
XS Rating Curve= 0 ,0
Exp/Cntr=0.3,0.1

Type RM Length L Ch R = 1 ,1151.9  ,202.9,196.6,190.4
XS GIS Cut Line= 3
     1730332.332      343944.948     1730213.115      343578.794
     1730015.714      343499.109
#Sta/Elev= 30
       0   844.2     9.6  842.66    48.1   839.9    96.3  839.16   163.7   836.9
   259.9  836.51   269.6  835.91   279.2  834.75   298.4  831.56   317.7   830.9
   327.3  832.61   332.7  835.58   336.9  837.91   346.6  844.28   365.8  855.51
   385.1  867.55   394.8     872   404.4  874.96   433.5  879.35   481.8  890.43
   491.5  891.78   501.2  893.58   510.9  894.96   520.5  895.72   530.2  897.15
   549.6  898.62   559.2  900.09   578.6  901.48   588.3  902.88     598   903.8
#Mann= 3 , 0 , 0
       0     .06       0   317.7    .045       0   332.7     .06       0
Bank Sta=317.7,332.7
XS Rating Curve= 0 ,0
Exp/Cntr=0.3,0.1

Type RM Length L Ch R = 1 ,955.3   ,676.6,697.4,718.1
XS GIS Cut Line= 4
     1730530.479      343957.732     1730487.212      343677.629
     1730400.511      343548.653     1730040.057      343497.236
#Sta/Elev= 30
       0  857.92    39.1  841.45    48.9   839.9    68.4   834.6    78.2   833.4
   107.5  831.31   136.8   830.4   166.2  830.52   205.2  832.26   234.6  832.87
   273.6   832.9   341.7  832.16   370.8  831.52   390.3  828.82   402.9  828.06
   409.7  827.61   417.9  828.38   497.9  833.11   527.4  836.02   576.6  846.01
   586.4  848.53   625.8  860.03   635.6  863.86   645.5  868.75   665.2   873.6
   694.7  879.89   724.2  885.07     734  887.54   763.6  891.19   802.9  898.05
#Mann= 3 , 0 , 0
       0     .08       0   402.9    .045       0   417.9     .08       0
#XS Ineff= 2 , 0
          278.25  832.98
Permanent Ineff=
       F       F
Bank Sta=402.9,417.9
XS Rating Curve= 0 ,0
Exp/Cntr=0.3,0.1

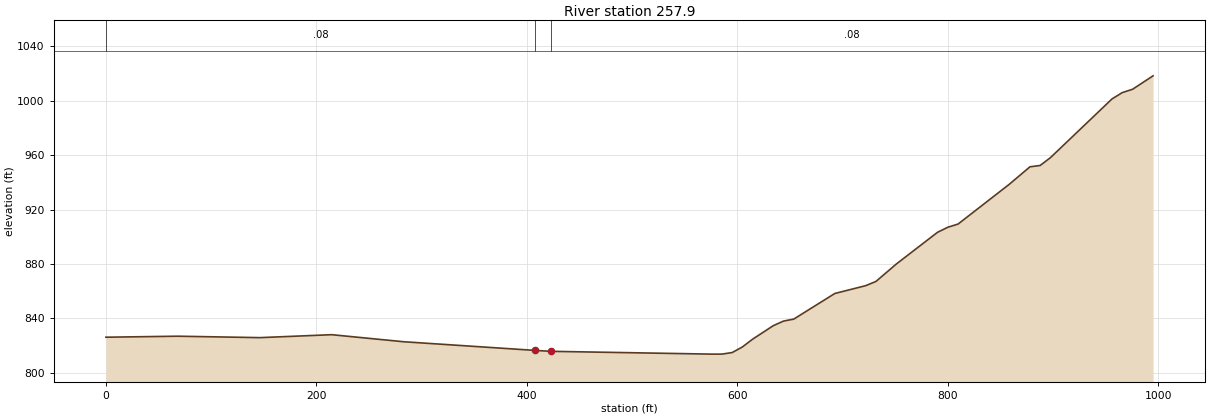
Type RM Length L Ch R = 1 ,257.9   ,248.8,257.9,267
XS GIS Cut Line= 2
     1730858.901      343679.645     1731165.589      342733.032
#Sta/Elev= 30
       0  826.23    68.3  826.97   146.3  825.92   214.6  828.08   282.9   822.9
   407.7  816.54   422.7  815.86   575.6   813.8   585.3  813.81   595.1  814.96
   604.8  819.08   614.6  824.83   634.1  834.69   643.9  838.09   653.6  839.53
   692.6  858.36   721.9   864.1   731.7  867.21   751.2  880.11   790.2  903.32
     800  907.04   809.7  909.37   858.5  938.68     878  951.44   887.7  952.44
   897.5  958.18     956 1001.34   965.8    1006   975.5 1008.42     995 1018.32
#Mann= 3 , 0 , 0
       0     .08       0   407.7    .045       0   422.7     .08       0
Bank Sta=407.7,422.7
XS Rating Curve= 0 ,0
Exp/Cntr=0.3,0.1

Chan Stop Cuts=-1
Use User Specified Reach Order=0
Composite Channel Slope=5